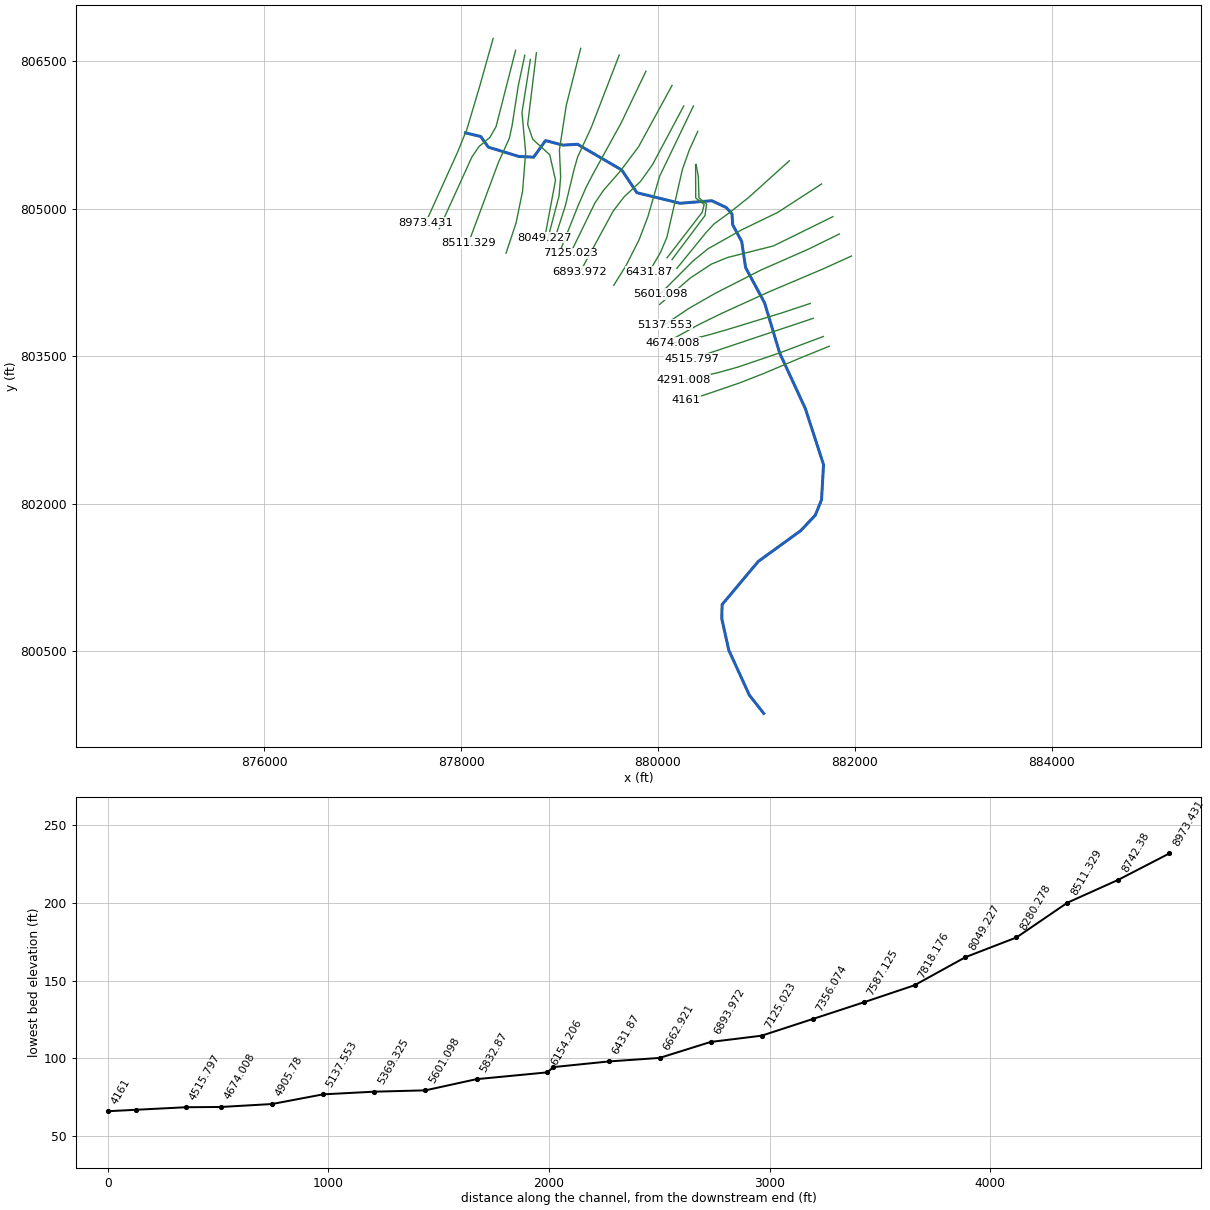
--- 11833_ras.prj (project) ---

Proj Title=11833
Current Plan=p01
Default Exp/Contr=0.3,0.1
English Units
Geom File=g01
Flow File=f01
Plan File=p01
Y Axis Title=Elevation
X Axis Title(PF)=Main Channel Distance
X Axis Title(XS)=Station
BEGIN DESCRIPTION:
RFD model 11833 exported to HEC-RAS
END DESCRIPTION:

--- 11833_ras.p01 (plan) ---

Plan Title=Plan 01
Program Version=4.10
Short Identifier=Plan 01
Geom File=g01
Flow File=f01
Subcritical Flow
Calc Critical at every XS
Secant Critical Depth

--- 11833_ras.f01 (steady flow) ---

Flow Title=Flow 01
Program Version=5.01
Number of Profiles= 6
Profile Names=10yr,25yr,50yr,100yr,100plus,500yr
River Rch & RM=11833,23,8973.431
 2817.44 3709.49 4419.78 4853.02 7085.42 6724.77
River Rch & RM=11833,23, 8742.38
  2839.7 3740.38 4457.87 4896.06 7148.25 6779.67
River Rch & RM=11833,23,8511.329
 2867.09 3778.66 4505.23 4949.77 7226.67 6848.64
River Rch & RM=11833,23,8280.278
 2874.27 3788.84 4517.95 4964.31 7247.89 6867.62
River Rch & RM=11833,23,8049.227
 2879.24 3795.89 4526.73 4974.33 7262.52 6880.66
River Rch & RM=11833,23,7818.176
 2935.56    3876 4626.92 5088.96 7429.88 7030.48
River Rch & RM=11833,23,7587.125
 2942.49 3885.92 4639.37 5103.25 7450.75 7049.27
River Rch & RM=11833,23,7356.074
 2950.35 3897.14 4653.44 5119.38 7474.29 7070.38
River Rch & RM=11833,23,7125.023
 2956.76 3906.35 4665.03  5132.7 7493.75 7087.95
River Rch & RM=11833,23,6893.972
 3476.28 4613.74 5527.05 6097.05 8901.69    8264
River Rch & RM=11833,23,6662.921
 3489.98 4634.12  5553.2 6127.62 8946.33 8304.75
River Rch & RM=11833,23, 6431.87
 3494.55 4640.85 5561.79 6137.62 8960.92 8317.95
River Rch & RM=11833,23,6181.201
 3503.47  4653.9  5578.4 6156.89 8989.06 8343.22
River Rch & RM=11833,23, 5832.87
  3660.9 4871.27 5845.64 6458.18 9428.94 8711.31
River Rch & RM=11833,23,5601.098
 3661.58 4872.31 5846.99 6459.77 9431.26 8713.47
Boundary for River Rch & Prof#=11833,23,1
Up Type= 0
Dn Type= 2
Boundary for River Rch & Prof#=11833,23,2
Up Type= 0
Dn Type= 2
Boundary for River Rch & Prof#=11833,23,2
Up Type= 0
Dn Type= 2
Boundary for River Rch & Prof#=11833,23,2
Up Type= 0
Dn Type= 2
Boundary for River Rch & Prof#=11833,23,2
Up Type= 0
Dn Type= 2
Boundary for River Rch & Prof#=11833,23,2
Up Type= 0
Dn Type= 2

--- 11833_ras.g01 (geometry) ---

Geom Title=11833
Program Version=4.10

River Reach=11833,23
Reach XY= 30
878043.878268629805769.308955986878199.318274885805731.765644756
878276.575219331805623.692728093 878586.90508044805529.074672541
878737.078691552805522.130228093878856.646549097805690.021448067
879035.759161403 805644.30932913879182.665339148 805653.23001355
879631.787431191805391.995687063879786.354321189805160.841088252
 880224.04069019805053.587031904880547.067998228805079.283328001
880693.675913776805010.845505872880751.835635998804945.741339205
880759.648135996804833.762172547880851.039527067 804664.98092873
880889.943441125 804401.18908256881083.581226856 804040.89457453
881236.447729023803532.458561568 881497.98720619802966.102472882
881682.238278001802398.463102494 881661.75492686802040.139436405
881598.455638739801884.395085557881450.486203048 801727.19971644
881018.680707368801414.279660013880651.457437575800976.333770814
880648.627915888800831.388708006880719.682428005800513.172912635
880928.780692041800055.737436334881074.368753621799870.877918712

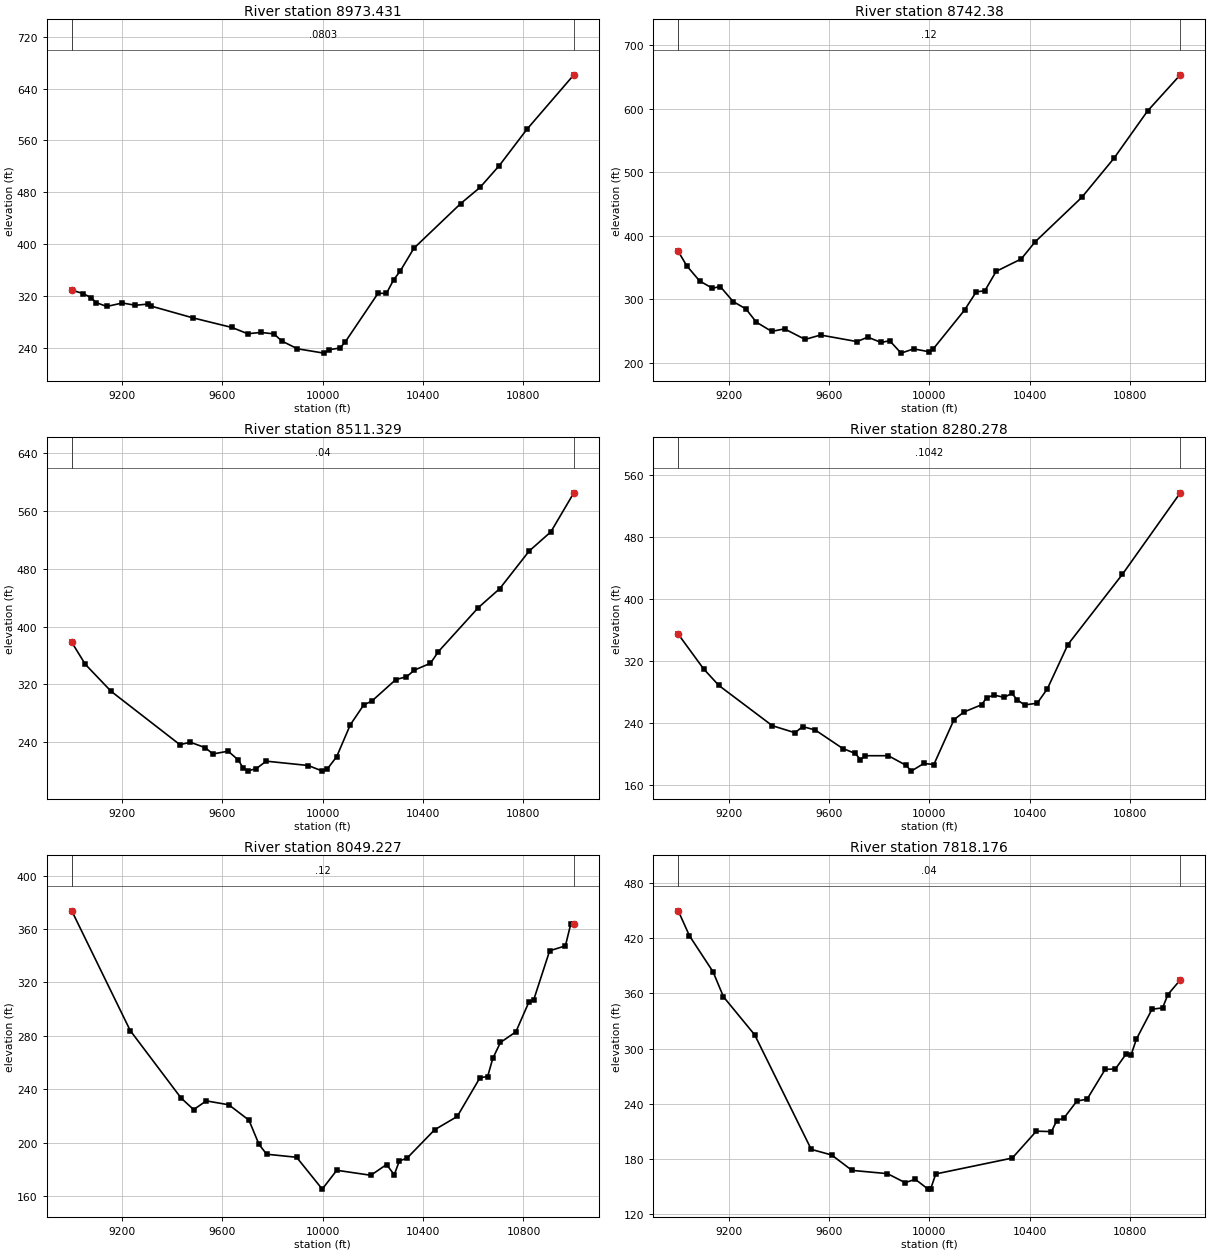
Type RM Length L Ch R = 1 ,8973.431,231.050900,231.050900,231.050900
XS GIS Cut Line= 6
878325.661790849806729.256415722878186.437441348806233.840897305
878053.820843044805788.609946223878034.469249537805747.289370389
877966.748041269805578.445653748877638.646074433804854.137207397
#Sta/Elev= 30
 8999.05328.84739045.021323.67299076.183317.17049096.958 309.6049138.508303.8098
9200.832309.10819252.769305.61439304.706307.51799315.093304.37749481.291286.2474
9637.798271.32979700.474261.71079752.704263.65319804.934261.51599836.272 250.492
 9898.72238.464410004.26231.764310026.31 237.05810069.08239.731910090.47249.5957
10220.58324.302310253.51323.787510282.76345.1171 10308.4358.223610363.29393.6506
10549.92 462.57810626.77487.409210703.61521.0894 10813.4576.943211000.97661.1993
#Mann= 3 , 0 , 0
 8999.05  0.0803       0 8999.05  0.0803       011000.97  0.0803       0
#XS Ineff= 2 , 0
       09782.769                       0
Bank Sta=8999.05,11000.97
Exp/Cntr=0.3,0.1

Type RM Length L Ch R = 1 , 8742.38,231.051000,231.051000,231.051000
XS GIS Cut Line= 6
878553.632084569806607.688811762878355.075412261805832.246680692
878292.262176126805722.365722698878181.152906645805629.252811754
878110.162292598805524.843076804877778.182064162 804795.37711036
#Sta/Elev= 30
8999.173375.06619032.812352.53999084.266328.50769135.719 316.9669166.591319.7103
    9218296.05319269.225284.39789310.204263.71249371.674249.02889422.898253.0212
9504.939236.40989566.581243.31659711.912232.98649754.671239.98759808.546231.5593
9842.115234.42669887.626214.81529937.727221.48229999.706216.996410015.37221.1834
10140.57282.560310187.38311.420610221.57312.896410266.56343.554310366.71363.1613
10421.88389.985810607.89460.072110736.03521.496710870.17596.098211000.89653.1294
#Mann= 3 , 0 , 0
8999.173    0.12       08999.173    0.12       011000.89    0.12       0
#XS Ineff= 2 , 0
       09803.938                       0
Bank Sta=8999.173,11000.89
Exp/Cntr=0.3,0.1

Type RM Length L Ch R = 1 ,8511.329,231.051000,231.051000,231.051000
XS GIS Cut Line= 6
878646.949234733806557.643056699878580.891020275806247.991628303
878517.743102903805841.864144572878489.580874348805712.586260469
878380.553621409805472.329216644878074.779375916804649.974040824
#Sta/Elev= 30
 8999.08378.36119053.097347.92589155.597310.63559430.342236.6556 9471.85240.0962
9531.527232.45599561.853223.82359622.504 227.6749662.938 215.5529683.155 203.921
9703.373200.76149733.741203.28279774.428213.85879942.069 207.8559998.656200.0692
10017.34202.749110055.19219.992910109.67264.232710163.31291.792610195.32296.9714
10291.14326.820710333.61330.659410365.46339.933810429.15 349.369   10461365.5637
10620.25426.488610705.32452.618510822.98504.828810909.22531.283511000.95585.3323
#Mann= 3 , 0 , 0
 8999.08    0.04       0 8999.08    0.04       011000.95    0.04       0
#XS Ineff= 2 , 0
       0    9817                       0
Bank Sta=8999.08,11000.95
Exp/Cntr=0.3,0.1

Type RM Length L Ch R = 1 ,8280.278,231.050900,231.050900,231.050900
XS GIS Cut Line= 6
878703.552909494806513.692242417878618.410486787805975.315596421
878655.687710513805568.730001463878624.543691649805176.322701468
878558.473056164804853.909576276878456.571178466804547.067020919
#Sta/Elev= 30
8999.126354.4161 9100.16309.67069161.299288.1948 9374.19236.3252 9464.83227.2196
9494.935235.17699545.108230.81829655.151206.87799705.205200.52399725.314192.5766
9745.481197.5808 9836.67197.58959907.965185.12779928.127177.70379978.179187.6021
10018.35186.233110098.61 244.08110138.69254.061910208.83263.352710228.86272.5531
   10259275.798210299.22272.808610329.38278.2067 10349.5 269.96610379.82263.0992
10430.42265.3461 10471.1284.024610552.82341.061710770.39431.767211000.96536.7762
#Mann= 3 , 0 , 0
8999.126  0.1042       08999.126  0.1042       011000.96  0.1042       0
#XS Ineff= 2 , 0
       09794.696                       0
Bank Sta=8999.126,11000.96
Exp/Cntr=0.3,0.1

Type RM Length L Ch R = 1 ,8049.227,231.051000,231.051000,231.051000
XS GIS Cut Line= 6
878764.834892677806582.605902719  878676.0285896805853.982490963
878727.845396374805703.697552175878900.182176233805547.057543136
878959.056383295805288.639703132878849.685210027804702.947800737
#Sta/Elev= 30
8999.237373.72329232.285283.9449 9434.87233.37369485.131224.66739535.334231.2237
9625.427228.27029705.572216.73949745.805198.50869776.274191.21899895.528188.9312
9997.726165.041710055.66179.179610191.56175.426710254.15183.493710284.82175.7869
10305.07 186.19810335.44188.208810445.68209.5408 10535.9219.525910626.64 248.624
10657.06249.432410677.51263.039210708.18275.033110769.52282.954610821.12305.1413
10840.27306.725610904.22343.749410967.09347.457410988.08363.623611000.72363.8422
#Mann= 3 , 0 , 0
8999.237    0.12       08999.237    0.12       011000.72    0.12       0
#XS Ineff= 2 , 0
       09854.972                       0
Bank Sta=8999.237,11000.72
Exp/Cntr=0.3,0.1

Type RM Length L Ch R = 1 ,7818.176,231.050900,231.050900,231.050900
XS GIS Cut Line= 6
879215.244415827806627.957468636879068.758052005806049.691960472
878998.812902173805596.333689439879011.134714532805320.920608343
 878995.30609977805129.292748643878873.690695597804668.063386228
#Sta/Elev= 30
8999.044449.83839043.861422.63799137.757 383.5379179.489356.23569303.788314.9069
9529.416190.21939610.838184.10139691.852167.36039833.208163.81519903.802153.9886
9944.141157.66079995.213146.961410005.51147.320410025.98163.486410330.83180.7651
10426.87210.044710487.28 209.56710507.43221.076810537.78 224.66310588.59242.7931
10629.29244.877910701.22277.242810742.33277.809910783.94293.719910804.77293.0415
10825.59 310.10910888.07342.759610930.27 344.22410951.37358.703511000.89374.7149
#Mann= 3 , 0 , 0
8999.044    0.04       08999.044    0.04       011000.89    0.04       0
#XS Ineff= 2 , 0
       0                               0
Bank Sta=8999.044,11000.89
Exp/Cntr=0.3,0.1

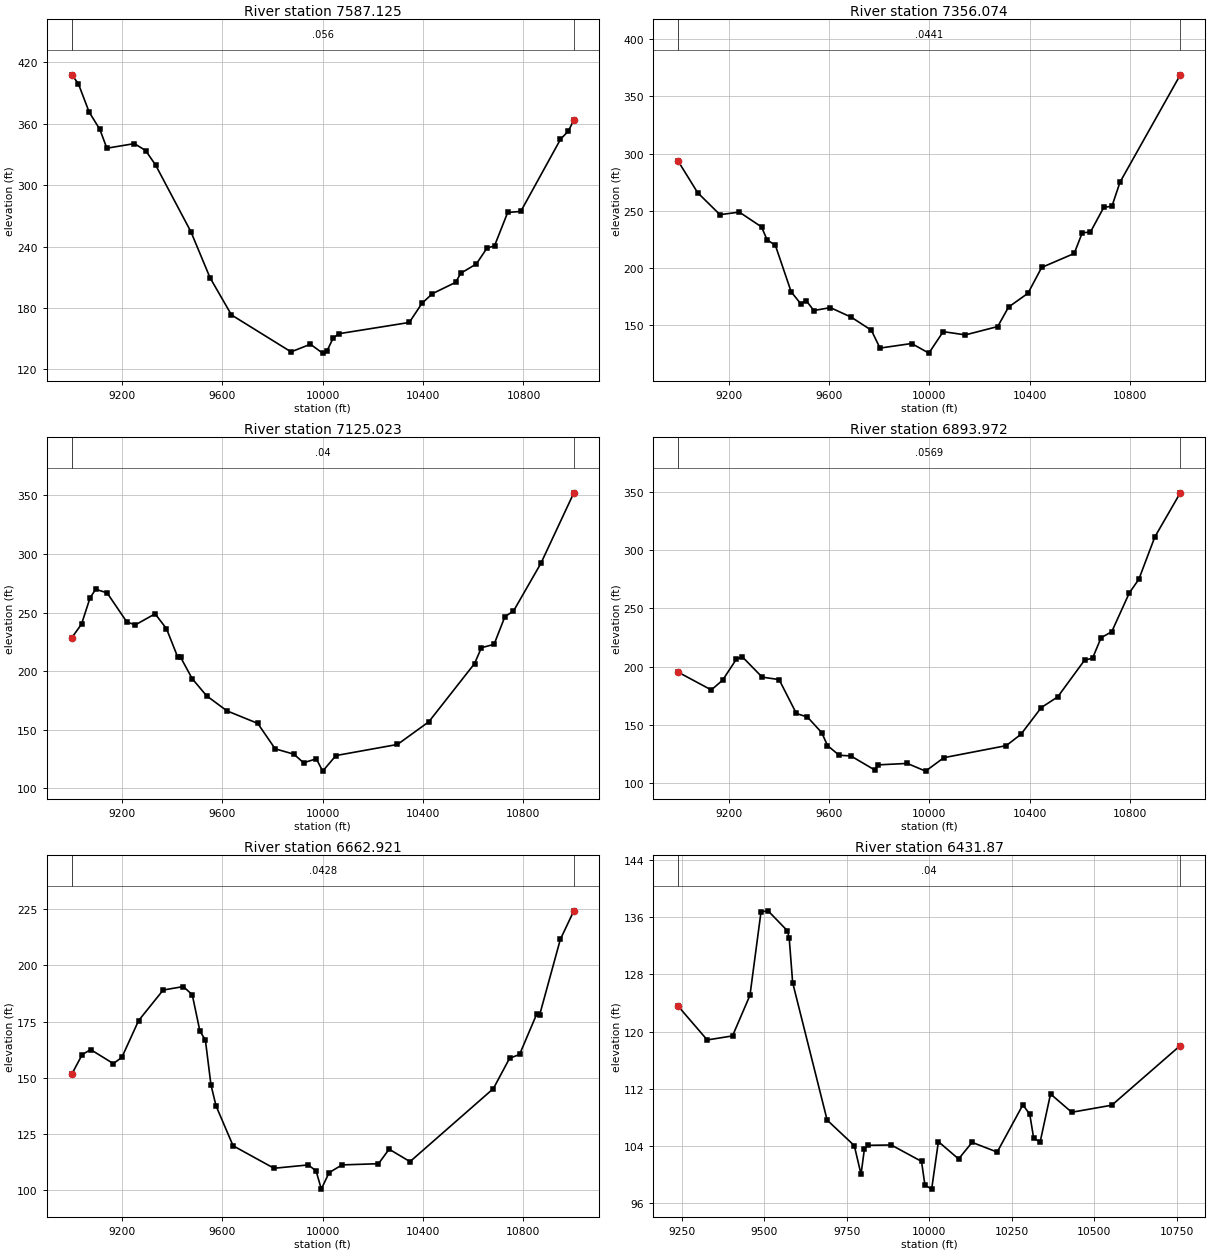
Type RM Length L Ch R = 1 ,7587.125,231.051000,231.051000,231.051000
XS GIS Cut Line= 6
879606.289046078806559.330432018879318.846864309805815.145895175
879184.254932669805525.406329026879147.865786517805398.325890361
879059.250842118805028.648329561878945.503964261804674.630980334
#Sta/Elev= 30
8999.039407.73419025.191399.15049068.185371.4284 9111.18354.34279138.917336.0618
9248.767 340.5649293.574333.7822 9333.26319.61299474.081 254.4849550.302 209.574
9635.877173.22389873.373137.16489950.677144.6201    9999135.9366 10016.2137.8479
10041.05 150.54210063.22154.856410344.57 165.87410395.88184.721310436.93194.0095
10529.55 205.03610550.19213.995910612.11222.992210653.65238.179410684.95240.9073
10737.12273.342210789.29274.311810947.61344.733210979.36352.954911000.91363.6885
#Mann= 3 , 0 , 0
8999.039   0.056       08999.039   0.056       011000.91   0.056       0
#XS Ineff= 2 , 0
       0                               0
Bank Sta=8999.039,11000.91
Exp/Cntr=0.3,0.1

Type RM Length L Ch R = 1 ,7356.074,231.050900,231.050900,231.050900
XS GIS Cut Line= 6
879877.972525595806395.573779133879624.636833936805866.893020283
 879334.10091234805339.752326076879268.484341396805211.950036203
879187.783530007805027.453831213879014.852541768804591.839320255
#Sta/Elev= 30
8999.018293.21429076.572265.68939165.376246.46969242.713248.70349331.099235.7466
9353.196224.52639386.523219.50469449.324178.89859486.964168.54749509.284171.2268
9539.424162.51729605.734165.0642 9689.49156.62219769.072145.25069803.473129.6217
9929.609133.63319998.411125.211210055.54144.025710144.01141.187410272.83148.4781
10316.21165.568610393.43177.614610448.24 200.25510577.88212.490610610.11230.6847
10642.33231.126910696.04252.961710728.26253.773510760.49274.922711000.97 368.936
#Mann= 3 , 0 , 0
8999.018  0.0441       08999.018  0.0441       011000.97  0.0441       0
#XS Ineff= 2 , 0
       0                               0
Bank Sta=8999.018,11000.97
Exp/Cntr=0.3,0.1

Type RM Length L Ch R = 1 ,7125.023,231.051000,231.051000,231.051000
XS GIS Cut Line= 6
880142.887985923806250.101783771879802.473942673805626.830910773
879613.591709493805375.677508645879450.628690713805189.820715209
879360.276994981805058.195916465879110.916893054804545.870846375
#Sta/Elev= 30
8999.037228.42689038.027240.12679072.304262.81099094.813269.8462 9139.83266.8035
 9218.61241.91989252.372239.44639331.387248.90679376.683236.18289421.978211.6753
9433.302211.65059478.944193.58289536.345178.91419617.578166.02069740.467 155.313
9809.924133.59119885.001128.97039923.182121.6599 9974.09125.03519999.525 114.521
10052.41127.823310297.71137.307410422.76156.682510605.16206.436410632.26219.9304
10682.89222.837310726.14246.535810760.24251.217810870.08292.247611000.94352.2549
#Mann= 3 , 0 , 0
8999.037    0.04       08999.037    0.04       011000.94    0.04       0
#XS Ineff= 2 , 0
       0                               0
Bank Sta=8999.037,11000.94
Exp/Cntr=0.3,0.1

Type RM Length L Ch R = 1 ,6893.972,231.050900,231.050900,231.050900
XS GIS Cut Line= 6
880261.872847658806041.984592229879943.727647388805444.406819875
879823.404921735805275.911312183879655.670968383805118.462321339
879546.111460932804976.073074969879208.502889724804354.869803082
#Sta/Elev= 30
8999.095195.33369130.884180.12939175.946 188.4849231.181206.63419254.805208.4789
9333.663191.11449401.256189.01869470.058159.95429514.246156.86879571.317143.4716
9594.187132.43049640.662124.12229687.479 123.5099782.828111.43439795.759115.8569
9912.236117.09969985.227110.493110058.43122.042510306.67132.337910365.66142.1036
 10446.7165.035710511.97174.151210619.54205.753810651.03207.330610684.87224.8726
10727.57230.091310797.68263.3784 10835.6275.072610899.21311.317811000.89349.1934
#Mann= 3 , 0 , 0
8999.095  0.0569       08999.095  0.0569       011000.89  0.0569       0
#XS Ineff= 2 , 0
       0                               0
Bank Sta=8999.095,11000.89
Exp/Cntr=0.3,0.1

Type RM Length L Ch R = 1 ,6662.921,231.051000,231.051000,231.051000
XS GIS Cut Line= 6
880360.355484747 806041.89318423880015.803226515805325.337913013
879897.170737267804915.434171558879807.275276913804680.202692595
879676.803166711 804423.12358816879551.005984723804219.757453845
#Sta/Elev= 30
8999.046151.51019040.663160.25899074.505162.46669164.751156.23829198.592158.9692
9265.576175.41789363.473 189.045 9443.63190.58319479.447  186.969509.821170.7965
9531.884166.68179553.948146.78759574.174137.40289642.202119.57549805.435109.5315
9942.396111.03189973.374108.29279994.026100.229510024.92107.551310076.43111.0362
10221.92111.563610264.36 118.05610347.69112.490910679.99145.068210744.59158.5802
10784.63160.3274   10853178.367310864.67177.997510946.95211.606211000.93224.3813
#Mann= 3 , 0 , 0
8999.046  0.0428       08999.046  0.0428       011000.93  0.0428       0
#XS Ineff= 2 , 0
       0                10273.59       0
Bank Sta=8999.046,11000.93
Exp/Cntr=0.3,0.1

Type RM Length L Ch R = 1 , 6431.87,250.668700,250.668700,250.668700
XS GIS Cut Line= 6
880404.641498134805784.388556075880317.726430321805593.471437695
880247.483505924805394.180968676880090.994992187804708.519056651
880025.313178366804553.555047237879909.944794705804356.097111133
#Sta/Elev= 30
9238.913123.53669326.765118.8243 9403.48119.38949456.379125.07629489.879136.7611
9511.279136.89789569.427134.12479575.284133.12159585.779126.85289690.332107.6101
9772.672104.03219793.087100.01589803.269103.54299813.451104.07469884.728104.1213
9976.511101.82439986.74898.5158410007.2297.9437310027.64104.590610088.92102.1657
10129.77104.490610205.83103.1286 10283.8109.746110304.73108.407810316.45105.0693
10336.13104.560410367.62  111.2610431.88108.703410553.35109.691210761.05118.0438
#Mann= 3 , 0 , 0
9238.913    0.04       09238.913    0.04       010761.05    0.04       0
#XS Ineff= 2 , 0
       0                10151.69       0
Bank Sta=9238.913,10761.05
Exp/Cntr=0.3,0.1

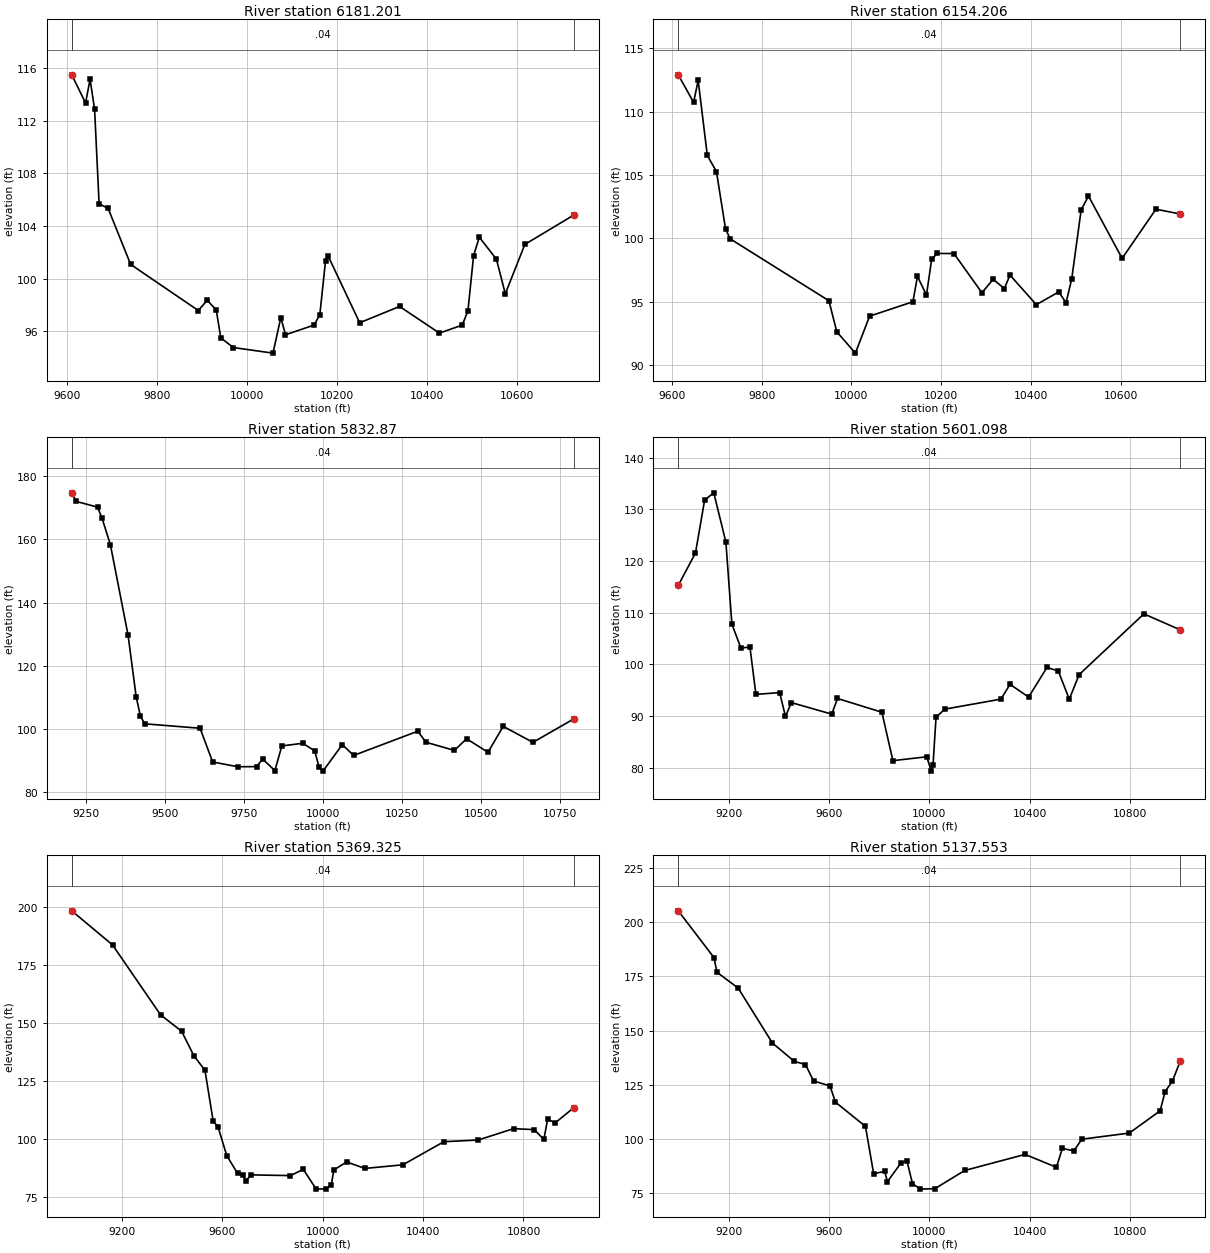
Type RM Length L Ch R = 1 ,6181.201,26.995500,26.995500,26.995500
XS GIS Cut Line= 5
880382.405660547805445.632070897 880383.70774389805107.090404241
 880469.64524383805041.986237554 880450.11399383804962.559154226
880092.041077203804499.017487554
#Sta/Elev= 30
 9611.48115.48549642.112113.34169652.112115.14879662.112112.86019672.112105.6795
9692.112105.33449742.113101.07179892.11497.567049912.11498.353069932.11497.58827
9942.11495.484729970.04694.7522610057.8494.3269810075.3397.0350810085.6395.72209
10149.1896.4618710161.8297.2504810174.45101.341510180.71101.674910250.27 96.6346
10338.7297.8761510427.1895.8483610477.7296.4560110490.3697.5375910502.99101.7455
10515.63103.137410553.54101.4763 10573.398.8374410616.72102.593510725.37104.8283
#Mann= 3 , 0 , 0
 9611.48    0.04       0 9611.48    0.04       010725.37    0.04       0
#XS Ineff= 2 , 0
       09686.265        10192.07       0
Bank Sta=9611.48,10725.37
Exp/Cntr=0.3,0.1

Type RM Length L Ch R = 1 ,6154.206,321.335800,321.335800,321.335800
XS GIS Cut Line= 6
880387.179966062805448.670265332880409.315382749805331.482765332
880417.127882719805107.524432003880493.950799406805045.024432003
880478.325799406804929.139015332880142.388299376804481.222348675
#Sta/Elev= 30
9613.899112.89339648.165110.72229658.341112.45179678.695106.53229699.049105.2663
9719.402100.73149729.57999.959269949.77395.072449967.40192.6197410008.7990.93965
10040.4893.8548510137.04 94.993210147.1396.9859910167.3195.5299910178.7798.33024
 10190.9 98.8022 10228.498.79692 10290.995.70269 10315.996.76132 10340.9 96.0332
 10353.497.09948 10412.1 94.7625 10462.195.76498 10478.4 94.9234 10490.996.75914
 10512.1102.2402 10528.4 103.333 10603.498.4140410678.77102.294210733.12101.9136
#Mann= 3 , 0 , 0
9613.899    0.04       09613.899    0.04       010733.12    0.04       0
#XS Ineff= 2 , 0
       09716.543        10205.76       0
Bank Sta=9613.899,10733.12
Exp/Cntr=0.3,0.1

Type RM Length L Ch R = 1 , 5832.87,231.772400,231.772400,231.772400
XS GIS Cut Line= 6
   881335.090193805485.447978666880924.434565887805115.246152963
880719.902157794804952.672561355880569.648681246804843.716506244
880485.015468154804751.755527733880192.270650927804392.506868093
#Sta/Elev= 30
9205.675174.75919219.367172.05659287.216170.21879300.786166.91339327.926158.2952
9383.861129.61829409.345110.19199422.914104.01129436.484101.5625 9611.59100.1531
9651.47889.462989731.25587.950139790.511 87.99679809.61590.387459848.328 86.7376
9870.33994.547099936.62295.39135 9974.5892.978459987.49588.0076910000.3986.56476
10061.7494.9625610097.69 91.538410300.1599.2009110326.5595.7148810416.3893.12469
10454.8396.8309310522.7392.5328810570.69100.752710664.8695.6845710794.27103.1236
#Mann= 3 , 0 , 0
9205.675    0.04       09205.675    0.04       010794.27    0.04       0
#XS Ineff= 2 , 0
       09927.516        10231.58       0
Bank Sta=9205.675,10794.27
Exp/Cntr=0.3,0.1

Type RM Length L Ch R = 1 ,5601.098,231.772500,231.772500,231.772500
XS GIS Cut Line= 6
881661.630367629805249.202002404881216.329500155804960.544455578
880847.068653912804781.752038508 880507.50902624804590.673686942
880351.835663498804463.166932797880020.914295636  804131.3008022
#Sta/Elev= 30
8999.079115.29589067.865121.57269104.305131.81129140.744133.2076 9189.02123.6891
9213.013107.81099249.004103.17459284.994103.38149308.76994.210519403.43294.56313
9426.71289.939159449.99292.628979611.25890.396069634.00893.423389811.04390.76342
9854.92481.395229989.90882.1442510008.0279.3699910014.8280.4881210026.9989.78852
10061.8591.3599110285.6493.2979810321.9496.1559510396.0793.6977910469.1999.42343
10514.3998.7405110558.2293.2816310597.69 98.0497 10855.6109.789611000.91106.6919
#Mann= 3 , 0 , 0
8999.079    0.04       08999.079    0.04       011000.91    0.04       0
#XS Ineff= 2 , 0
       09891.585        10194.14       0
Bank Sta=8999.079,11000.91
Exp/Cntr=0.3,0.1

Type RM Length L Ch R = 1 ,5369.325,231.772400,231.772400,231.772400
XS GIS Cut Line= 6
881777.487285382804917.493369839 881172.14743201804619.758621192
880707.028400856804502.599573004880544.346084971804436.097472202
880331.779331097804296.714417845880017.056769161 804025.47442368
#Sta/Elev= 30
8999.076198.24779161.612183.58869353.196153.48379436.691146.48849485.962135.9017
9530.083129.64679562.883107.7829 9582.09105.3254    961792.943299660.29485.23991
9681.80684.716629692.44181.908939713.71284.648769871.03284.327049922.23187.03849
9972.97878.6241810013.5678.5125610033.8680.4160810044.0186.7600510095.1190.20721
10167.5487.4199210319.0788.9666810482.5898.9139810619.5699.6417910760.56104.5303
10842.94104.122410881.3799.88477 10896.4108.618910926.46107.004711000.91113.5668
#Mann= 3 , 0 , 0
8999.076    0.04       08999.076    0.04       011000.91    0.04       0
#XS Ineff= 2 , 0
       09905.464        10222.06       0
Bank Sta=8999.076,11000.91
Exp/Cntr=0.3,0.1

Type RM Length L Ch R = 1 ,5137.553,231.772500,231.772500,231.772500
XS GIS Cut Line= 6
881842.539930071804741.263970732881528.833006926804587.325280553
881049.445896912804376.573920954880578.897307697 804137.10409985
880311.786668101803983.958244838880068.862950935803820.490953456
#Sta/Elev= 30
8999.019205.26959141.881 183.6369153.082176.93949237.788169.6327 9374.63144.2217
9462.402135.74289506.144134.32939538.792126.72579604.086124.43269625.851116.9474
9745.557105.75649778.20483.909429822.131 84.99539833.116  80.2619888.33989.05849
9910.71789.903539933.09579.309079964.84776.7983210022.6877.0259110141.1585.40702
10382.0792.8260310506.9486.8783510530.57 95.595710576.2294.4759410608.6599.85501
10797.59 102.66710920.49112.952910940.37 121.84410969.15126.613311000.95135.9021
#Mann= 3 , 0 , 0
8999.019    0.04       08999.019    0.04       011000.95    0.04       0
#XS Ineff= 2 , 0
       09887.556        10318.18       0
Bank Sta=8999.019,11000.95
Exp/Cntr=0.3,0.1

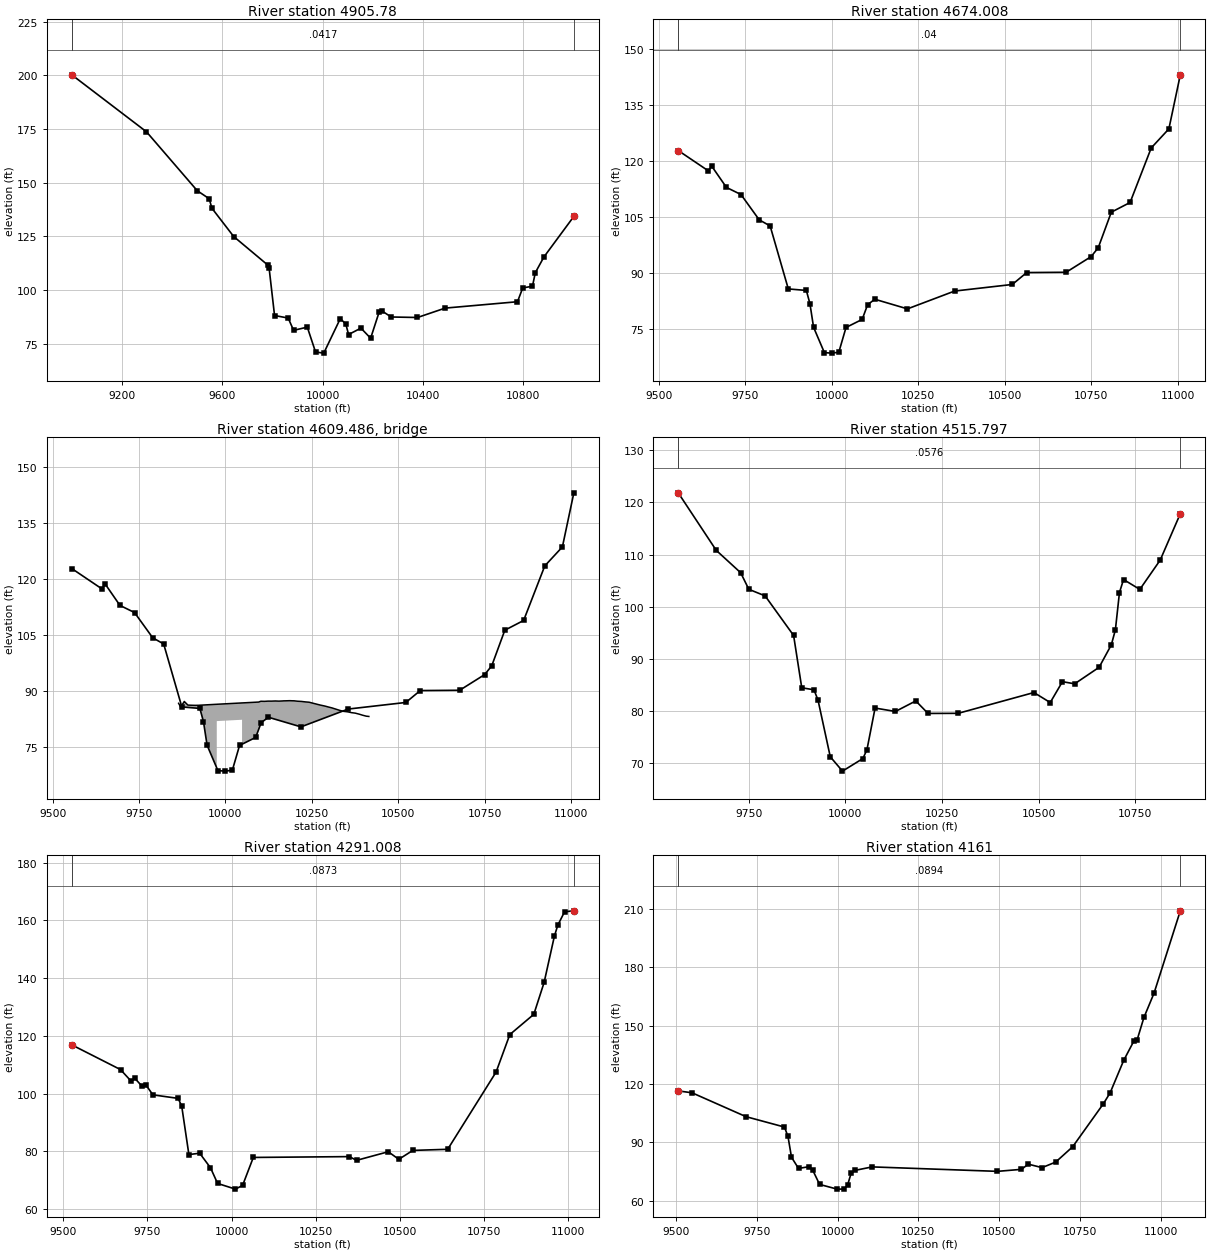
Type RM Length L Ch R = 1 , 4905.78,231.772400,231.772400,231.772400
XS GIS Cut Line= 6
881966.267820368804517.497787663881673.271979157804384.658399261
 881135.54907122804156.846282735880648.090730632803935.468549308
880407.496619553803817.298444888880151.503628478803675.159328181
#Sta/Elev= 30
8999.014200.2272 9296.93173.68259499.293146.25039546.918142.50079557.778138.0789
9644.661124.89519781.275111.53379785.847110.24319807.56888.09446 9861.87  86.914
9883.59181.171449938.15382.68639 9970.9971.0935510003.8470.5666310069.7986.66096
10091.7784.0903110102.76 79.239510152.0782.2145210190.6977.5017910224.3689.60716
10234.66 90.315310272.5587.4048110377.5487.1679110487.85  91.54510776.2394.51421
 10797.3100.964410835.96101.712210847.32 108.04710881.75115.386411000.99 134.258
#Mann= 3 , 0 , 0
8999.014  0.0417       08999.014  0.0417       011000.99  0.0417       0
#XS Ineff= 2 , 0
       09836.748        10192.29       0
Bank Sta=8999.014,11000.99
Exp/Cntr=0.3,0.1

Type RM Length L Ch R = 1 ,4674.008,158.210900,158.210900,158.210900
XS GIS Cut Line= 6
881547.277586233804035.629271795  881259.1809122803939.939071512
880705.532084492803770.637348144880515.333439511803716.090226494
880389.092263787 803684.33714958880152.545343721803635.050515624
#Sta/Elev= 30
9555.523122.8631 9642.22117.45179652.757118.63349694.906113.00159737.055111.0913
9789.741104.33159821.352102.69039873.89485.846949926.07285.444079936.50781.88251
9946.94375.600929978.24968.81031 9999.1268.6771810019.9668.9107810040.8175.54187
10087.5277.6958210103.34 81.637710124.1983.0864310218.5180.5121610354.7785.27645
10521.85 87.044210563.4690.2260110677.5390.3046810749.71 94.491510770.31 96.8531
10808.14106.373310862.49108.971110923.67123.564710974.66128.651111007.76143.1128
#Mann= 3 , 0 , 0
9555.523    0.04       09555.523    0.04       011007.76    0.04       0
#XS Ineff= 2 , 0
       09910.734        10118.74       0
Bank Sta=9555.523,11007.76
Exp/Cntr=0.3,0.1

Type RM Length L Ch R = 3 ,4609.486,,,
BEGIN DESCRIPTION:
END DESCRIPTION:
Bridge Culvert--1,0,-1,-1, 0
Deck Dist Width WeirC Skew NumUp NumDn MinLoCord MaxHiCord MaxSubmerge Is_Ogee
69.755450,18.700000,2.6,0, 60, 60, , , 0.95, 0, 0,0,,
 9864.55 9870.43 9880.95 9880.96 9891.49 9902.02 9912.56 9912.83 9923.09 9927.68
 9974.94 9974.9410048.1010048.1010095.9610102.1310104.0910112.6610123.1910133.72
10135.9610144.2510154.7810165.3210167.8410175.8510186.3810193.7910197.0910198.00
10208.2410219.3910220.6310230.5310241.6810243.2710252.8310263.9710265.9110275.12
10286.2710288.5410297.4110308.5610311.1810319.7110330.8510333.8210342.0010353.15
10356.4510364.2910375.4410379.0910386.5910396.4310397.6310406.8310407.8910414.80
   86.82   85.82   87.30   87.31   86.34   86.30   86.27   86.27   86.29   86.32
   86.56   86.56   86.92   86.92   87.15   87.36   87.36   87.34   87.40   87.40
   87.41   87.44   87.40   87.45   87.47   87.49   87.52   87.49   87.49   87.49
   87.38   87.32   87.31   87.20   87.11   87.08   86.85   86.59   86.54   86.33
   86.11   86.06   85.84   85.58   85.50   85.25   84.92   84.85   84.66   84.54
   84.48   84.32   84.19   84.10   83.92   83.64   83.61   83.39   83.37   83.30
 -913.18 -914.18 -912.70 -912.69 -913.66 -913.70 -913.73 -913.73 -913.71 -913.68
 -913.44   82.06   82.42 -913.08 -912.85 -912.64 -912.64 -912.66 -912.60 -912.60
 -912.59 -912.56 -912.60 -912.55 -912.53 -912.51 -912.48 -912.51 -912.51 -912.51
 -912.62 -912.68 -912.69 -912.80 -912.89 -912.92 -913.15 -913.41 -913.46 -913.67
 -913.89 -913.94 -914.16 -914.42 -914.50 -914.75 -915.08 -915.15 -915.34 -915.46
 -915.52 -915.68 -915.81 -915.90 -916.08 -916.36 -916.39 -916.61 -916.63 -916.70
 9864.55 9870.43 9880.95 9880.96 9891.49 9902.02 9912.56 9912.83 9923.09 9927.68
 9971.97 9971.9710045.1310045.1310095.9610102.1310104.0910112.6610123.1910133.72
10135.9610144.2510154.7810165.3210167.8410175.8510186.3810193.7910197.0910198.00
10208.2410219.3910220.6310230.5310241.6810243.2710252.8310263.9710265.9110275.12
10286.2710288.5410297.4110308.5610311.1810319.7110330.8510333.8210342.0010353.15
10356.4510364.2910375.4410379.0910386.5910396.4310397.6310406.8310407.8910414.80
   86.82   85.82   87.30   87.31   86.34   86.30   86.27   86.27   86.29   86.32
   86.54   86.54   86.90   86.90   87.15   87.36   87.36   87.34   87.40   87.40
   87.41   87.44   87.40   87.45   87.47   87.49   87.52   87.49   87.49   87.49
   87.38   87.32   87.31   87.20   87.11   87.08   86.85   86.59   86.54   86.33
   86.11   86.06   85.84   85.58   85.50   85.25   84.92   84.85   84.66   84.54
   84.48   84.32   84.19   84.10   83.92   83.64   83.61   83.39   83.37   83.30
 -913.18 -914.18 -912.70 -912.69 -913.66 -913.70 -913.73 -913.73 -913.71 -913.68
 -913.46   82.04   82.40 -913.10 -912.85 -912.64 -912.64 -912.66 -912.60 -912.60
 -912.59 -912.56 -912.60 -912.55 -912.53 -912.51 -912.48 -912.51 -912.51 -912.51
 -912.62 -912.68 -912.69 -912.80 -912.89 -912.92 -913.15 -913.41 -913.46 -913.67
 -913.89 -913.94 -914.16 -914.42 -914.50 -914.75 -915.08 -915.15 -915.34 -915.46
 -915.52 -915.68 -915.81 -915.90 -916.08 -916.36 -916.39 -916.61 -916.63 -916.70
BR Coef=-1 , 0 , 0 ,, 0 ,,,0.8,0,1,0,
WSPro=,,,, 1 ,,,, 0 ,,,, 0 ,,,,-1 ,-1 ,-1 , 0 , 0 , 0 , 0 , 0
BC Design=,, 0 ,, 0 ,,,,,,

Type RM Length L Ch R = 1 ,4515.797,224.789100,224.789100,224.789100
XS GIS Cut Line= 2
 881578.26234682803884.896081352880345.623457931803472.569692463
#Sta/Elev= 30
9567.223121.85179665.565110.83099728.833106.53879749.922103.36179792.101102.0995
9865.91494.511339887.00384.485979918.63784.099729929.18182.095689960.81571.25776
9992.44968.5090210045.1770.9192910055.72  72.59610076.8180.5965210129.5379.94437
10182.2581.9666110213.89 79.565710291.92 79.587210488.0583.5747210530.2381.65325
10561.8685.6540810593.4985.2446110656.7688.41015 10688.492.7132110698.9495.60251
10709.48102.745610720.03105.232710762.21103.341610814.93108.9593   10867117.8543
#Mann= 3 , 0 , 0
9567.223  0.0576       09567.223  0.0576       0   10867  0.0576       0
#XS Ineff= 2 , 0
       09918.987        10118.78       0
Bank Sta=9567.223,10867
Exp/Cntr=0.3,0.1

Type RM Length L Ch R = 1 ,4291.008,130.007900,130.007900,130.007900
XS GIS Cut Line= 6
881680.522556888803700.219518077881237.055420653803533.783388483
880819.599750676803391.442697385880623.499309398803336.084667961
880492.134689807803304.972491362880257.838506044803261.510487383
#Sta/Elev= 30
9525.322116.8538  9670.2108.28459702.272104.20649712.962105.22559734.343102.4934
9745.033103.06799766.37599.540289841.24698.318499851.93695.696559873.31778.85498
9905.38879.318689937.40274.301699958.66368.8511910011.7666.8845810032.9568.18673
10064.7477.8593810350.3678.1465910371.3876.8455610465.7479.8348410497.0477.21486
10538.7280.2966210642.3180.6793110786.13107.435110826.89120.414310898.23127.4312
 10928.8138.455510959.27 154.452 10969.4158.296410989.66 162.95811017.18163.2772
#Mann= 3 , 0 , 0
9525.322  0.0873       09525.322  0.0873       011017.18  0.0873       0
#XS Ineff= 2 , 0
       0                10268.44       0
Bank Sta=9525.322,11017.18
Exp/Cntr=0.3,0.1

Type RM Length L Ch R = 1 ,    4161,0.000000,0.000000,0.000000
XS GIS Cut Line= 6
881739.824570013803600.592642853881454.605466302 803485.24649118
881075.172514194803324.427851279880835.280618117803230.386295074
880482.860900949803109.343544438880287.145564842 803049.77720339
#Sta/Elev= 30
9506.548116.47619549.248115.50989716.566103.21459835.52197.875539846.38993.02527
9857.25782.337019878.99276.598219911.59677.476819922.46475.889869944.19968.37034
9998.539 65.936610020.2665.9679710031.1168.1438410041.9774.1139110052.82 75.5525
 10107.177.3754710494.92 75.083210569.3176.1178310590.5778.7778210633.0876.99966
10675.3179.8518710727.9887.74884 10822.8 109.81410843.86115.466710885.79132.1336
10917.17142.069610927.63142.806410948.54154.254910979.92166.800511061.23209.1411
#Mann= 3 , 0 , 0
9506.548  0.0894       09506.548  0.0894       011061.23  0.0894       0
#XS Ineff= 2 , 0
       0                10377.24       0
Bank Sta=9506.548,11061.23
Exp/Cntr=0.3,0.1